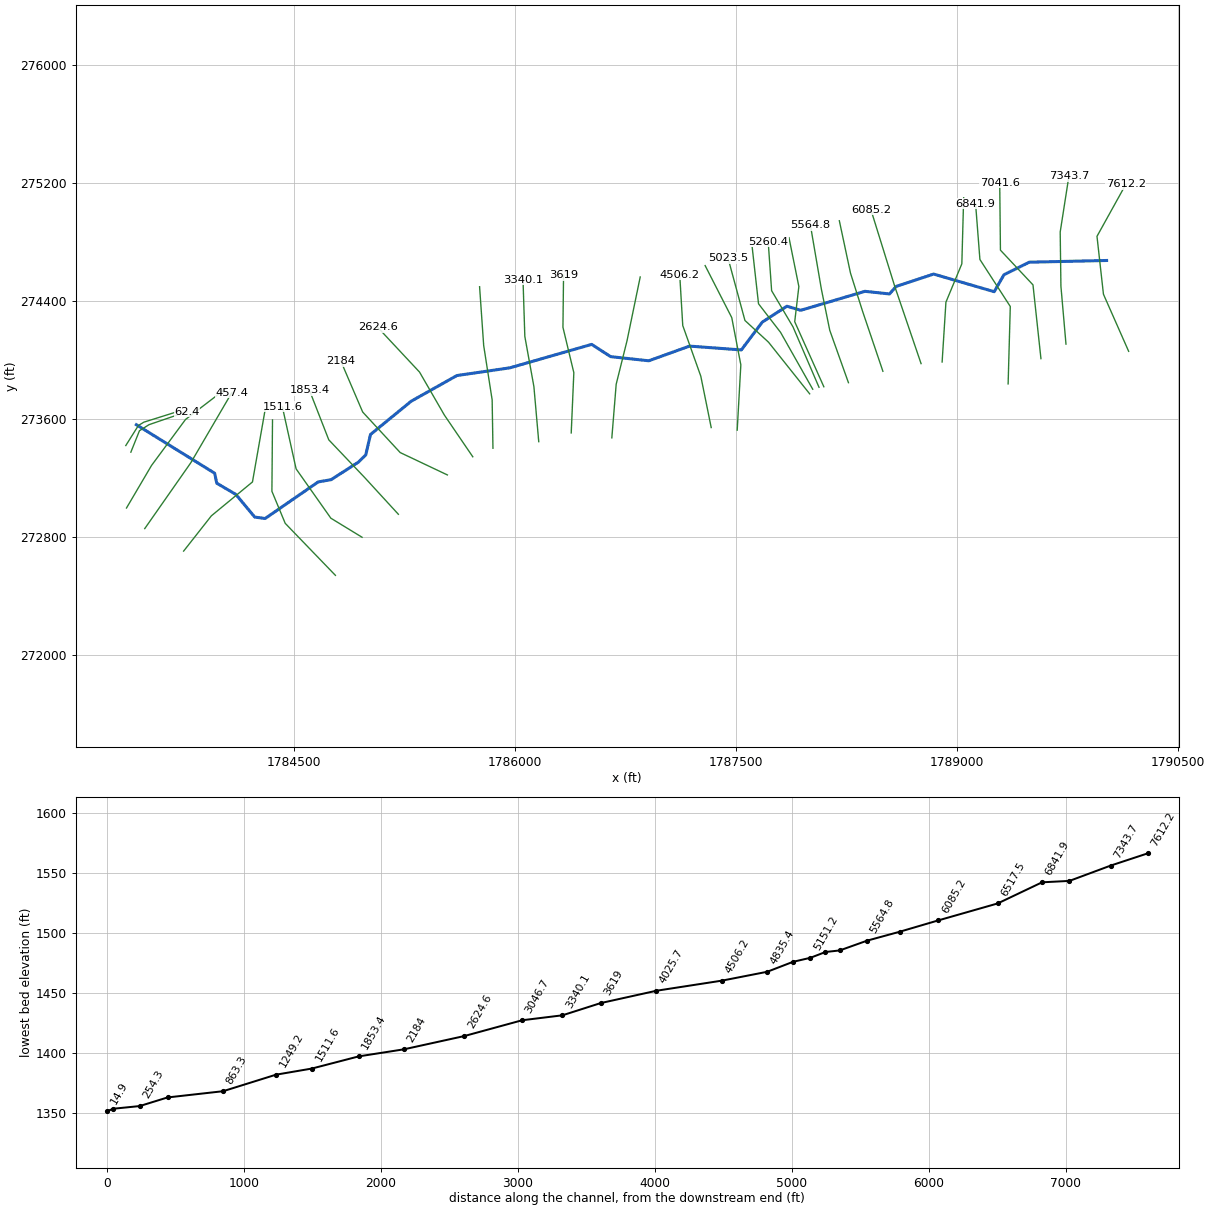
--- StraightFk.prj (project) ---

Proj Title=StraightFk
Current Plan=p01
Default Exp/Contr=0,0
English Units
Geom File=g01
Flow File=f01
Plan File=p01
BEGIN DESCRIPTION:
END DESCRIPTION:
DSS Export Rating Curves= 0
DSS Export Rating Curve Sorted= 0
DSS Export Volume Flow Curves= 0
DXF OffsetX= 0
DXF OffsetY= 0
DXF ScaleX= 0
DXF ScaleY= 0

--- StraightFk.p01 (plan) ---

Plan Title=Floodplain
Program Version=4.00
Geom File=g01
Flow File=f01
K Sum by GR=0
Std Step Tol=0.01
Critical Tol=0.01
Num of Std Step Trials=20
Max Error Tol=0.3
Flow Tol Ratio=0.001
Split Flow NTrial=30
Split Flow Tol=0.02
Split Flow Ratio=0.02
Log Output Level=0
Friction Slope Method=1
Unsteady Friction Slope Method=2
Unsteady Bridges Friction Slope Method=1
Global Log Level=0
CheckData=False
Run HTab=0
Run UNet=0
Run PostProcess=0
UNET Theta=0
UNET Theta Warmup=0
UNET ZTol=0
UNET ZSATol=0
UNET MxIter=0
UNET MaxInSteps=0
UNET DtIC=0
UNET DtMin=0
UNET MaxCRTS=0
UNET WFStab=0
UNET SFStab=0
UNET WFX=0
UNET SFX=0
UNET DSS MLevel=0
UNET DZMax Abort=0
UNET Convert EG Bridges=0
UNET Use Existing IB Tables=0
UNET Froude Limit=0
UNET Froude Power=0
Write IC File=0
Echo Input=False
Echo Output=False
Write Detailed=0

--- StraightFk.f01 (steady flow) ---

Flow Title=NFF Regression Equation
Program Version=4.00
Number of Profiles=1
Profile Names=P100yr
River Rch & RM=StraightFk,Main      ,7612.2
559.4117
River Rch & RM=StraightFk,Main      ,7041.6
586.5940
River Rch & RM=StraightFk,Main      ,5151.2
637.2658
River Rch & RM=StraightFk,Main      ,4506.2
945.8989
River Rch & RM=StraightFk,Main      ,1249.2
1003.737
River Rch & RM=StraightFk,Main      ,863.3
1360.119
River Rch & RM=StraightFk,Main      ,254.3
1364.786
Boundary for River Rch & Prof#=StraightFk,Main      ,1
Up Type=0
Dn Type=3
Dn Slope=0.03142

--- StraightFk.g01 (geometry) ---

Geom Title=USGS 10m DEM
Program Version=4.00

River Reach=StraightFk      ,Main
Reach XY= 30
     1790014.111      274675.169     1789489.623      274663.553
      1789318.07       274578.67      1789251.95      274463.408
     1788840.912      274583.042     1788586.288      274499.148
     1788541.613      274448.218     1788375.141      274465.954
     1787939.503      274337.243     1787845.713       274364.98
     1787678.485      274257.008     1787536.418      274068.478
      1787185.27       274094.39     1786908.635       273994.75
     1786650.059      274022.909     1786521.394      274106.005
     1785966.527      273946.961     1785607.258      273894.709
     1785297.696      273720.807     1785021.197      273494.847
     1784989.031      273356.353     1784938.994       273307.21
     1784754.038      273188.374     1784666.475      273173.184
     1784306.392       272924.79     1784235.804      272934.618
     1784108.033      273088.301     1783978.475      273164.249
     1783964.147      273231.987     1783432.894      273561.117

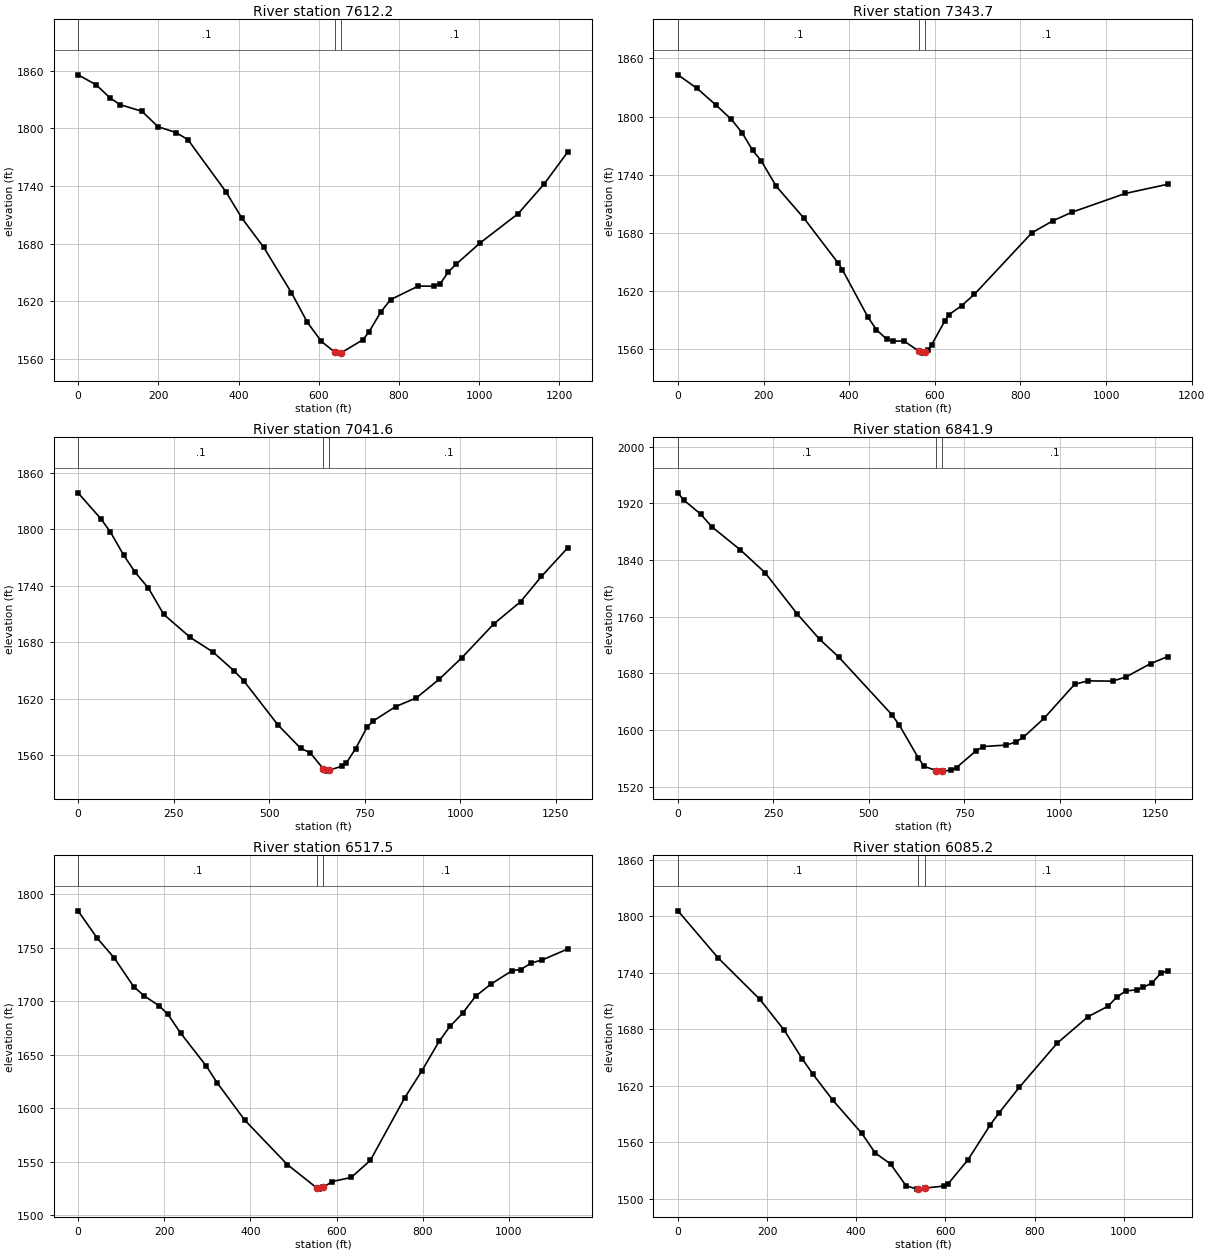
Type RM Length L Ch R = 1 ,7612.2  ,270.7,268.4,266.2
XS GIS Cut Line= 4
     1790163.774      274058.945     1789992.786       274446.24
     1789948.908      274838.951     1790144.111      275190.901
#Sta/Elev= 30
       0  1855.6    44.8 1845.32    79.7 1831.67   104.6 1824.59   159.4 1817.67
   199.2 1801.63     244 1795.61   273.9 1788.14   368.6 1733.96   408.4 1706.52
   462.9 1676.14     532 1628.89   571.5 1598.23   606.1 1578.47   640.7 1566.89
   650.6 1566.12   655.7 1566.42   709.8 1579.99   724.7 1587.84   754.3 1608.66
     779 1621.79   848.3 1635.91   888.1 1635.68     903 1638.45   922.9 1650.63
   942.7 1658.74  1002.4 1680.83  1096.8 1711.14  1161.4 1741.87    1221 1775.59
#Mann= 3 , 0 , 0
       0      .1       0   640.7    .045       0   655.7      .1       0
Bank Sta=640.7,655.7
XS Rating Curve= 0 ,0
Exp/Cntr=0.3,0.1

Type RM Length L Ch R = 1 ,7343.7  ,284.9,302.1,319.6
XS GIS Cut Line= 4
     1789738.655      274107.852     1789704.315      274500.315
     1789699.409       274868.25     1789758.278      275245.996
#Sta/Elev= 30
       0 1843.15    44.9 1829.05    89.8 1811.56   124.7 1797.19   149.6 1783.55
   174.5 1765.16   194.5  1754.4   229.4 1728.27   294.2 1695.26     374 1649.01
     384 1642.12   443.7 1593.16   463.6 1580.13   488.4 1570.12   503.4 1568.44
   528.2 1568.48   562.5 1558.08     573 1556.02   577.5    1557   582.9 1558.89
   592.9 1564.92   622.7 1588.77   632.6 1595.55   662.5 1604.97   692.3 1616.66
   826.5 1680.12   876.1 1692.66   920.8 1701.48  1044.9 1720.76  1144.2 1730.29
#Mann= 3 , 0 , 0
       0      .1       0   562.5    .045       0   577.5      .1       0
Bank Sta=562.5,577.5
XS Rating Curve= 0 ,0
Exp/Cntr=0.3,0.1

Type RM Length L Ch R = 1 ,7041.6  ,204.4,199.7,194.7
XS GIS Cut Line= 4
     1789568.783       274009.38      1789514.82      274509.771
     1789294.059      274745.249     1789289.153      275201.488
#Sta/Elev= 30
       0 1838.52    59.8 1810.99    84.7 1796.98   119.6 1772.34   149.5  1754.2
   184.4 1737.38   224.2 1709.55     294 1685.03   353.8 1669.44   408.6 1649.51
   433.5 1639.17   523.2 1592.31   582.8 1567.42   607.6 1562.76   642.5 1545.41
   652.3 1543.22   657.5 1544.24     692 1548.63   701.9 1551.62   726.8 1567.22
   756.6 1589.85   771.4 1596.09     831 1611.61   885.6 1620.92   945.1 1640.59
  1004.6 1663.56  1088.9 1699.65  1158.4 1723.03  1212.9 1749.75  1282.3 1780.39
#Mann= 3 , 0 , 0
       0      .1       0   642.5    .045       0   657.5      .1       0
Bank Sta=642.5,657.5
XS Rating Curve= 0 ,0
Exp/Cntr=0.3,0.1

Type RM Length L Ch R = 1 ,6841.9  ,346.4,324.4,302.3
XS GIS Cut Line= 4
     1789346.192      273838.033     1789360.909      274362.953
     1789154.866       274681.83     1789125.431      275059.576
#Sta/Elev= 30
       0 1934.81    14.9 1924.71    59.4 1904.81    89.2 1886.69   163.5 1854.32
   227.9 1822.28   312.1 1764.19   371.6 1727.94   421.1 1703.21   560.1 1621.96
   580.1 1606.99     630 1560.48     645 1548.74   676.6 1542.91   691.6 1542.08
     695 1542.05     715 1543.44   729.9 1547.04   779.9  1570.2   799.9 1576.78
   859.8 1578.78   884.8 1583.05   904.8 1589.68   959.6 1616.72  1039.4 1664.54
  1074.3 1669.42  1139.1 1669.07    1174 1674.98  1238.8 1693.86  1283.7 1703.79
#Mann= 3 , 0 , 0
       0      .1       0   676.6    .045       0   691.6      .1       0
Bank Sta=676.6,691.6
XS Rating Curve= 0 ,0
Exp/Cntr=0.3,0.1

Type RM Length L Ch R = 1 ,6517.5  ,416.2,432.2,447.7
XS GIS Cut Line= 4
     1788898.526      273986.419     1788924.294      274392.388
     1789032.221      274652.395     1789044.582      275100.646
#Sta/Elev= 30
       0  1784.6    44.6 1759.01    84.3 1740.39     129 1713.81   153.8 1705.03
   188.5 1695.69   208.4 1687.87   238.1 1670.27   297.6  1639.5   322.4 1624.07
   386.9 1588.89   485.8 1547.35   554.1 1525.51   559.9 1524.43   569.1  1526.1
   589.5 1531.53     634 1535.33   678.4  1551.4   758.1 1609.87   797.9  1635.1
   837.8 1662.56   862.7 1676.47   892.6 1688.97   922.5 1704.76   957.4 1715.91
  1007.2 1728.66  1027.1 1729.73    1052 1735.85  1076.9 1738.67  1136.7 1749.03
#Mann= 3 , 0 , 0
       0      .1       0   554.1    .045       0   569.1      .1       0
Bank Sta=554.1,569.1
XS Rating Curve= 0 ,0
Exp/Cntr=0.3,0.1

Type RM Length L Ch R = 1 ,6085.2  ,285,283.8,283
XS GIS Cut Line= 3
     1788755.723      273975.516     1788577.809      274497.611
     1788415.199      275020.476
#Sta/Elev= 30
       0 1805.66    89.4 1756.03   183.9 1711.65   238.5 1678.93   278.3 1648.89
   303.1 1632.14   347.8 1604.51   412.4 1569.63   442.3 1548.82     477 1537.04
   511.8  1513.9   536.7 1510.36   539.2 1510.43   554.2 1511.49   596.4  1513.6
   606.3  1516.1   651.1 1541.77   700.9 1578.74   720.8  1591.5   765.6 1618.26
   850.2 1664.95   919.9 1693.27   964.7 1704.38   984.6 1714.08  1004.6 1720.64
  1029.4 1721.81  1044.4 1724.54  1064.3 1729.37  1084.2 1739.99  1099.1 1741.78
#Mann= 3 , 0 , 0
       0      .1       0   539.2    .045       0   554.2      .1       0
Bank Sta=539.2,554.2
XS Rating Curve= 0 ,0
Exp/Cntr=0.3,0.1

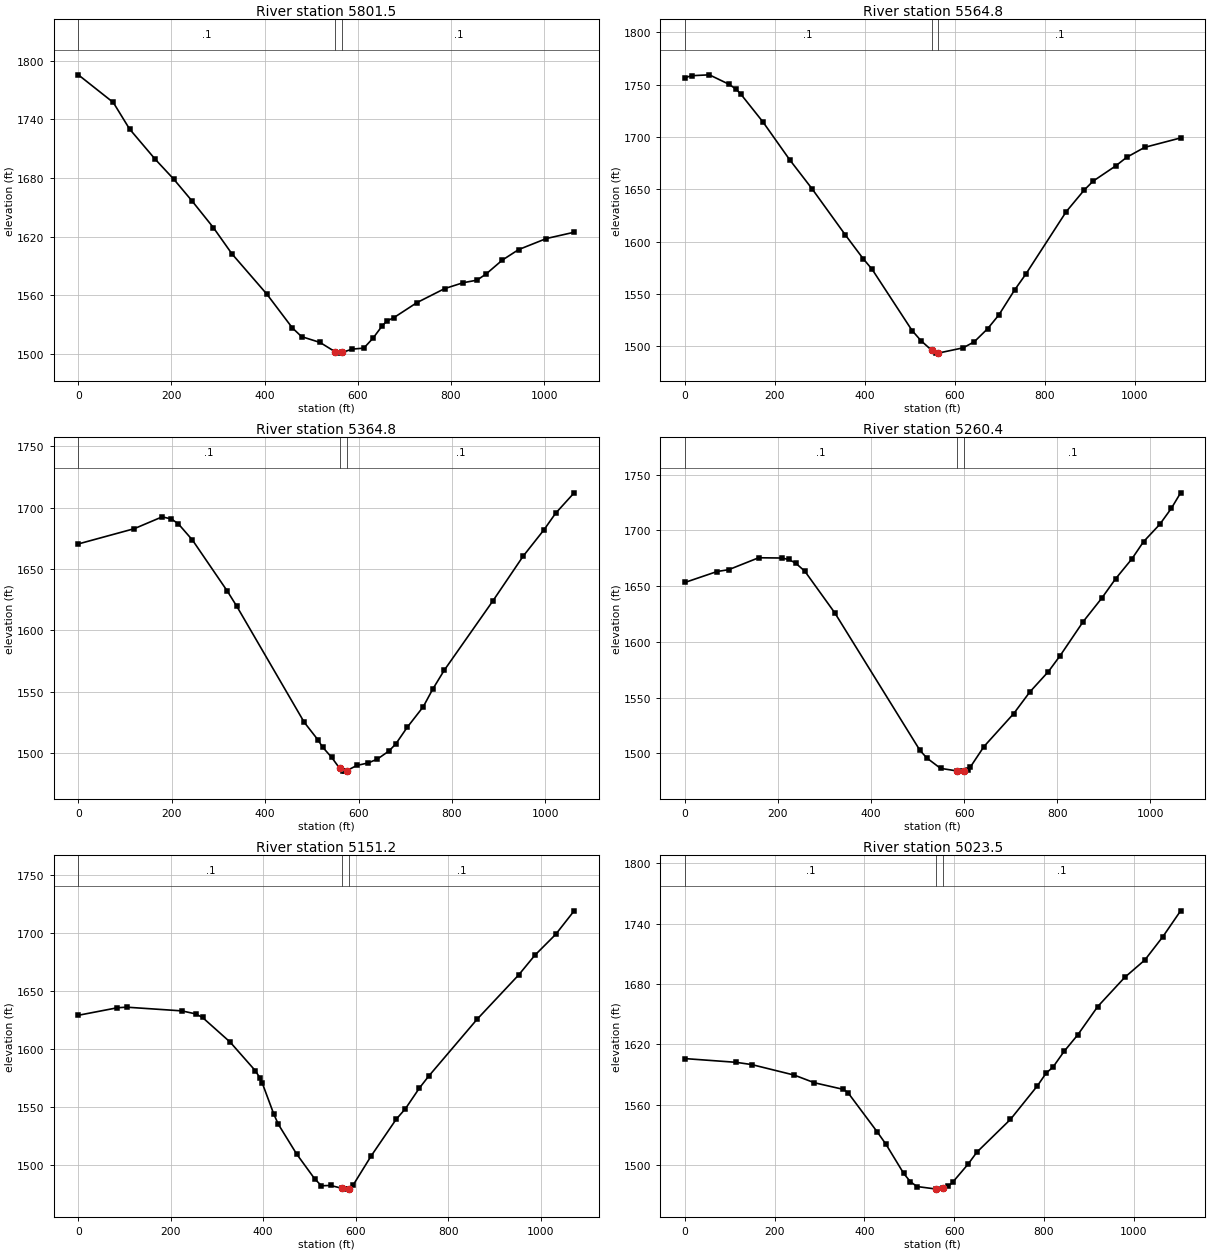
Type RM Length L Ch R = 1 ,5801.5  ,239.1,236.7,234.3
XS GIS Cut Line= 4
     1788496.837      273923.481     1788358.936      274330.615
     1788276.852         274590.     1788201.336      274944.601
#Sta/Elev= 30
       0 1785.36      75 1757.11     110 1729.96   164.9 1699.13   204.9 1678.66
   244.9 1655.95   289.9 1629.18   329.9 1602.27   404.9 1561.05   459.5 1526.63
   479.3  1517.7   518.9 1511.76   551.9 1502.06   558.5 1500.84   566.9 1501.65
   588.2 1504.95   612.9 1505.95   632.7 1516.14   652.4 1528.74   662.3 1533.63
   677.2 1537.04   726.8 1552.44   786.4  1566.8   826.1 1572.82   855.9 1575.44
   875.7 1581.84   910.5 1596.03   945.3  1606.7  1004.9    1618  1064.5 1624.44
#Mann= 3 , 0 , 0
       0      .1       0   551.9    .045       0   566.9      .1       0
Bank Sta=551.9,566.9
XS Rating Curve= 0 ,0
Exp/Cntr=0.3,0.1

Type RM Length L Ch R = 1 ,5564.8  ,207,200,193
XS GIS Cut Line= 4
     1788263.062      273846.322     1788136.436      274201.302
     1788079.195      274481.978     1788005.161      274914.797
#Sta/Elev= 30
       0 1756.67    14.9 1758.66    54.6 1759.51    99.2 1750.28   114.1 1745.71
     124 1741.35   173.6 1714.56   233.1 1678.38   282.7  1650.7     357 1606.43
   396.6 1583.72   416.4 1573.62   505.3 1515.08     525 1505.42   548.9 1496.17
   559.6 1493.46   563.9 1493.52   618.9 1498.52   643.6  1504.3   673.3 1516.81
   698.3 1529.98   733.2 1553.77   758.2 1568.98     848 1628.68   887.9 1649.29
   907.8 1657.87   957.7 1672.34   982.7 1680.73  1022.6  1690.2  1102.4 1699.19
#Mann= 3 , 0 , 0
       0      .1       0   548.9    .045       0   563.9      .1       0
Bank Sta=548.9,563.9
XS Rating Curve= 0 ,0
Exp/Cntr=0.3,0.1

Type RM Length L Ch R = 1 ,5364.8  ,89.1,104.4,119.6
XS GIS Cut Line= 4
     1788096.269      273818.413     1787898.644      274259.909
     1787926.699      274498.375     1787859.868      274829.684
#Sta/Elev= 30
       0 1670.33   119.7 1682.74   179.5 1692.37   199.5 1690.65   214.4 1686.59
   244.4 1673.48   319.2 1631.82   339.1 1619.68   483.7 1525.12   513.1 1510.78
   522.9 1504.96   542.5  1496.5   559.6  1487.6     567 1485.32   571.9 1485.31
   574.6 1485.63   596.4 1489.94   620.9 1491.98   640.5 1495.15     665 1501.63
   679.7 1507.38   704.2 1520.94   738.7 1537.77   758.6 1551.85   783.5 1567.41
   887.8 1623.96   952.4 1660.28   997.2 1681.85    1022 1695.27  1061.8 1711.95
#Mann= 3 , 0 , 0
       0      .1       0   559.6    .045       0   574.6      .1       0
Bank Sta=559.6,574.6
XS Rating Curve= 0 ,0
Exp/Cntr=0.3,0.1

Type RM Length L Ch R = 1 ,5260.4  ,106.5,109.2,111.9
XS GIS Cut Line= 4
     1788063.435       273815.13     1787886.954      274224.841
     1787742.004       274470.32     1787718.684      274803.417
#Sta/Elev= 30
       0 1653.29    69.4 1663.15    94.2 1664.78   158.6 1675.49   208.2 1675.26
     223 1673.97   237.9 1670.76   257.8 1663.44   322.2 1626.03   505.1 1502.65
   519.8 1495.82   549.3 1486.49   584.7 1484.17   588.6 1483.99   599.7 1484.38
   608.3 1485.28   613.2 1487.53   642.7 1506.09   706.6 1535.65   741.2 1555.05
     781 1573.31   805.9 1587.38   855.8 1618.18   895.6 1639.18   925.6 1656.73
   960.4 1674.47   985.4 1689.91  1020.2 1705.42  1045.2 1719.86  1065.1 1733.77
#Mann= 3 , 0 , 0
       0      .1       0   584.7    .045       0   599.7      .1       0
Bank Sta=584.7,599.7
XS Rating Curve= 0 ,0
Exp/Cntr=0.3,0.1

Type RM Length L Ch R = 1 ,5151.2  ,123.9,127.7,131.6
XS GIS Cut Line= 4
     1788020.752      273801.997      1787802.79      274187.434
     1787653.164       274381.48     1787610.334      274764.017
#Sta/Elev= 30
       0 1629.27    84.6 1635.77   104.5 1636.26   223.9 1633.07   253.7 1630.48
   268.7 1627.37   328.4 1606.14   383.1 1581.36     393 1575.11     398 1570.73
   422.9 1543.96   432.8 1535.11   472.2 1509.58   511.4 1488.06   526.1 1482.07
   545.7 1482.38   571.3 1479.81     580 1479.19   586.3 1479.54   594.7 1482.75
   633.9 1508.03   687.8 1539.54   707.8 1548.64   737.8 1566.35   757.8 1576.59
   862.8 1625.84   952.8 1664.12   987.8  1681.1  1032.8 1699.09  1072.8 1719.44
#Mann= 3 , 0 , 0
       0      .1       0   571.3    .045       0   586.3      .1       0
Bank Sta=571.3,586.3
XS Rating Curve= 0 ,0
Exp/Cntr=0.3,0.1

Type RM Length L Ch R = 1 ,5023.5  ,203.1,188.1,173
XS GIS Cut Line= 4
     1788000.027      273770.578     1787720.875      274120.945
     1787561.083      274268.232     1787446.166      274691.783
#Sta/Elev= 30
       0 1605.75   114.5 1602.02   149.3 1599.75   243.9 1589.29   288.7 1581.67
   353.4 1575.06   363.4 1571.81   428.1 1533.04     448 1520.47   487.5 1491.42
   502.3 1483.23   517.1 1478.39   560.4 1475.85   561.6 1475.81   575.4 1476.45
   586.3 1478.54   596.2 1482.48   630.7 1500.58   650.5 1512.62   725.1 1545.17
     785 1578.48   804.9 1591.37   819.9 1597.21   844.8 1612.97   874.8 1629.19
   919.6 1657.55   979.5 1686.48  1024.4 1703.81  1064.3 1726.86  1104.2 1752.81
#Mann= 3 , 0 , 0
       0      .1       0   560.4    .045       0   575.4      .1       0
Bank Sta=560.4,575.4
XS Rating Curve= 0 ,0
Exp/Cntr=0.3,0.1

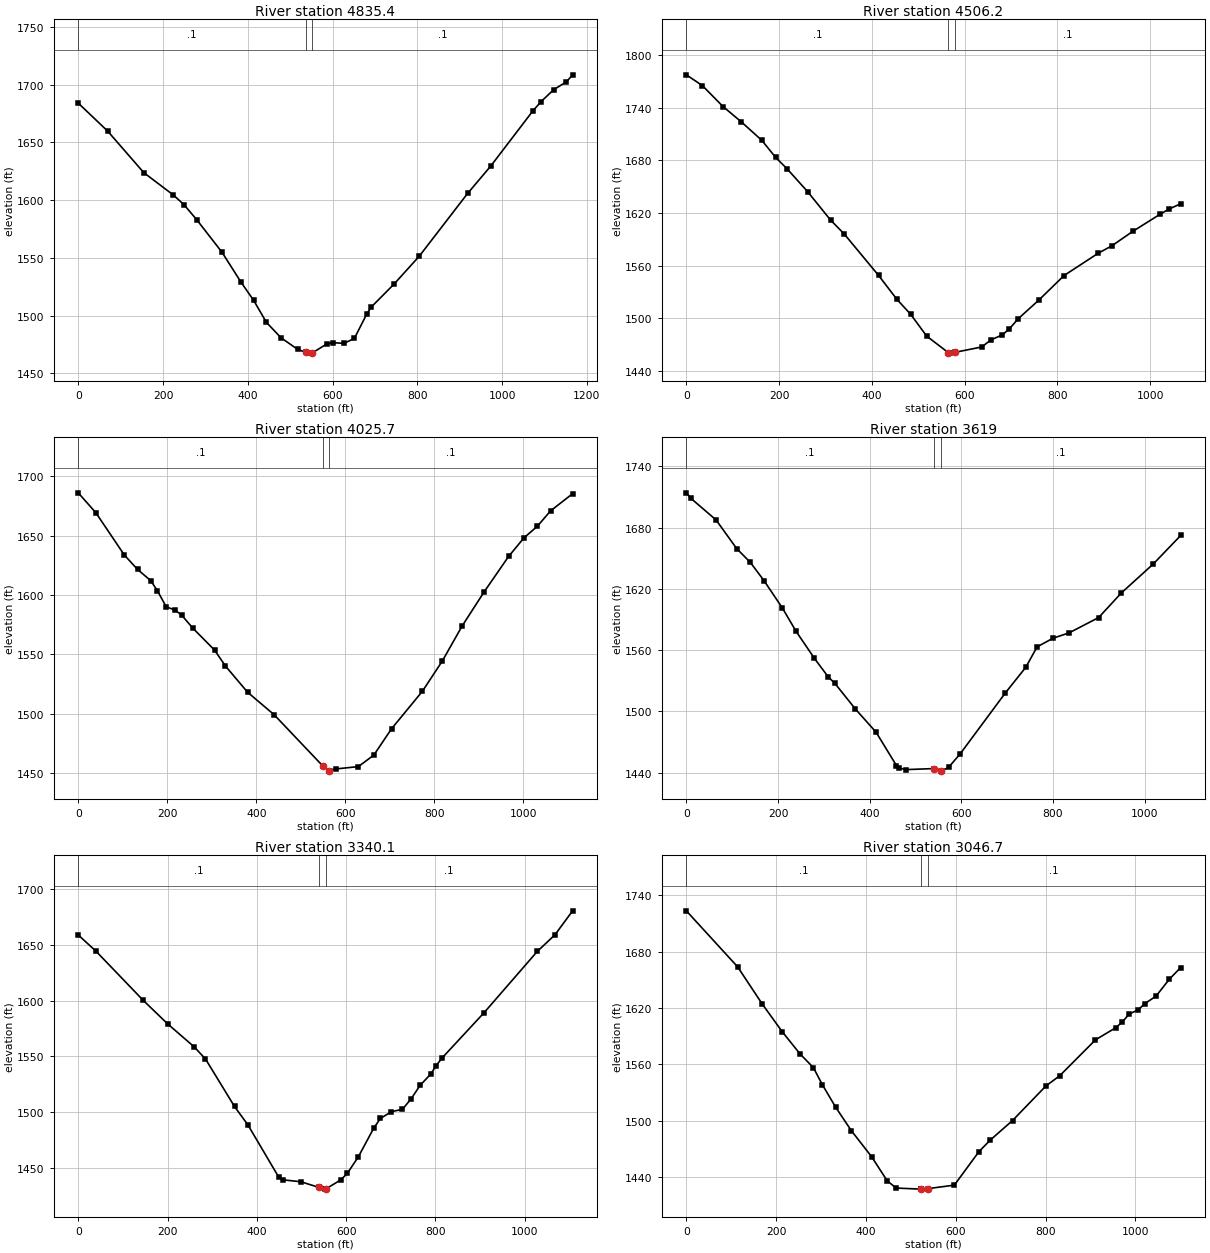
Type RM Length L Ch R = 1 ,4835.4  ,325.5,329.3,333
XS GIS Cut Line= 4
      1787508.55      273524.144     1787533.175      273967.395
     1787471.612      274287.521     1787291.028      274640.481
#Sta/Elev= 30
       0  1683.9    69.8  1659.5   154.6 1623.73   224.5 1604.33   249.4 1596.02
   279.3 1583.09   339.2 1554.81   384.1 1528.89     414 1513.11   443.9 1494.17
   478.5 1480.79     518  1470.7   536.6 1468.32   547.7 1467.53   551.6 1467.59
   587.2 1475.66     602 1476.58   626.7 1475.96   651.4 1480.22     681 1501.58
   690.9 1507.27   745.2 1527.33   804.6 1551.43   918.6 1605.71   973.1 1629.37
  1072.2 1676.96  1092.1 1685.22  1121.8 1695.57  1151.5 1702.21  1166.4 1708.38
#Mann= 3 , 0 , 0
       0      .1       0   536.6    .045       0   551.6      .1       0
Bank Sta=536.6,551.6
XS Rating Curve= 0 ,0
Exp/Cntr=0.3,0.1

Type RM Length L Ch R = 1 ,4506.2  ,493.9,480.4,466.9
XS GIS Cut Line= 4
     1787332.223       273541.82     1787261.647      273890.115
     1787139.173      274234.167     1787118.653      274578.918
#Sta/Elev= 30
       0 1777.51    34.6 1765.22      79 1741.37   118.5 1723.91   162.9 1702.72
   192.5 1683.35   217.2 1670.36   261.6 1644.22     311 1611.87   340.6 1595.91
   414.6 1548.69   454.1 1521.43   483.7 1504.42   518.2 1479.57   564.8 1460.77
   567.6 1460.17   579.8 1461.14   636.7 1467.17   656.4 1475.04   681.1 1481.04
   695.9 1487.45   715.6  1499.4     760 1520.63   814.3  1548.6   888.3 1574.16
   917.9 1582.67   962.3 1598.91  1021.5 1618.54  1041.3 1624.62  1065.9 1630.46
#Mann= 3 , 0 , 0
       0      .1       0   564.8    .045       0   579.8      .1       0
Bank Sta=564.8,579.8
XS Rating Curve= 0 ,0
Exp/Cntr=0.3,0.1

Type RM Length L Ch R = 1 ,4025.7  ,394.7,406.7,418.7
XS GIS Cut Line= 4
     1786658.153      273471.843     1786687.714      273836.061
     1786761.212      274130.792      1786850.63      274563.314
#Sta/Elev= 30
       0 1686.24    39.5 1669.47   103.7 1633.75   133.3 1621.68     163 1612.16
   177.8 1603.78   197.5 1590.24   217.3 1587.44   232.1 1583.31   256.8 1572.46
   306.2 1553.72   330.8 1540.26   380.4 1518.22   440.1 1499.25   549.5 1456.04
   564.5 1451.72   564.6 1451.71   579.5 1453.58   629.3 1455.51   664.2 1465.24
   703.9 1487.39   773.4 1519.08     818 1544.51   862.7 1574.12   912.3 1602.94
   966.9 1632.59  1001.7  1648.4  1031.4 1658.01  1061.2 1671.02  1110.8 1685.51
#Mann= 3 , 0 , 0
       0      .1       0   549.5    .045       0   564.5      .1       0
Bank Sta=549.5,564.5
XS Rating Curve= 0 ,0
Exp/Cntr=0.3,0.1

Type RM Length L Ch R = 1 ,3619    ,280.3,278.9,277.6
XS GIS Cut Line= 4
      1786382.71      273505.481     1786400.421      273914.041
     1786326.545      274221.855      1786330.65      274574.814
#Sta/Elev= 30
       0 1713.97      10 1708.54    64.8 1687.45   109.7 1659.43   139.6 1645.84
   169.6 1627.87   209.5 1601.19   239.4 1578.34   279.3 1551.92   309.2 1533.92
   324.2 1527.29     369 1502.13   413.9 1479.58   458.4 1446.87   463.4 1444.62
   478.2  1442.9   540.1 1443.93   555.1 1441.76   557.3 1441.43   572.2 1445.21
   596.9 1458.03   695.8 1517.93   740.4 1543.04   765.3 1563.16   800.1 1571.61
   834.9 1576.81   899.5 1591.82   949.2 1616.01  1018.8 1644.33  1078.5 1672.22
#Mann= 3 , 0 , 0
       0      .1       0   540.1    .045       0   555.1      .1       0
Bank Sta=540.1,555.1
XS Rating Curve= 0 ,0
Exp/Cntr=0.3,0.1

Type RM Length L Ch R = 1 ,3340.1  ,293.9,293.4,292.9
XS GIS Cut Line= 4
     1786162.378      273446.164     1786129.545      273819.645
     1786067.982      274160.292      1786055.67      274546.085
#Sta/Elev= 30
       0 1658.75      40 1644.12     145 1600.43     200 1579.25     260 1558.46
   284.9 1547.77   349.9 1505.24   379.9 1488.78   449.1 1441.88     459 1439.56
   498.6 1437.85   539.3 1432.78     553 1431.26   554.3 1431.42   587.6 1439.43
   602.4 1445.27   627.1 1460.08   661.7 1485.83   676.6 1494.51   701.3 1500.57
     726 1502.71   745.8 1512.28   765.6  1524.2   790.4 1534.65   800.3 1541.27
   815.1  1548.8   909.1 1589.32  1027.9 1644.01  1067.5 1658.89  1107.1 1680.38
#Mann= 3 , 0 , 0
       0      .1       0   539.3    .045       0   554.3      .1       0
Bank Sta=539.3,554.3
XS Rating Curve= 0 ,0
Exp/Cntr=0.3,0.1

Type RM Length L Ch R = 1 ,3046.7  ,413.6,422.1,430.5
XS GIS Cut Line= 4
     1785851.817      273401.658     1785846.356      273729.353
     1785788.898      274098.729     1785761.146      274497.262
#Sta/Elev= 30
       0 1723.35   114.2 1663.75   168.8 1624.36   213.5 1594.72   253.2 1571.08
     283 1556.48   302.9 1538.35   332.7 1514.26   367.6 1489.32   412.5 1461.78
   447.4 1436.02   467.3  1428.3   522.1 1427.16   522.7 1427.17   537.7 1427.68
   596.9  1431.4   651.7 1467.04   676.6 1479.23   726.5 1500.17   801.4 1537.18
   831.4 1547.73   911.3 1586.04   956.2 1598.87   971.2 1605.05   986.2 1613.51
  1006.2  1617.9  1021.2  1624.6  1046.1 1632.52  1076.1 1650.74  1101.1 1663.02
#Mann= 3 , 0 , 0
       0      .1       0   522.7    .045       0   537.7      .1       0
Bank Sta=522.7,537.7
XS Rating Curve= 0 ,0
Exp/Cntr=0.3,0.1

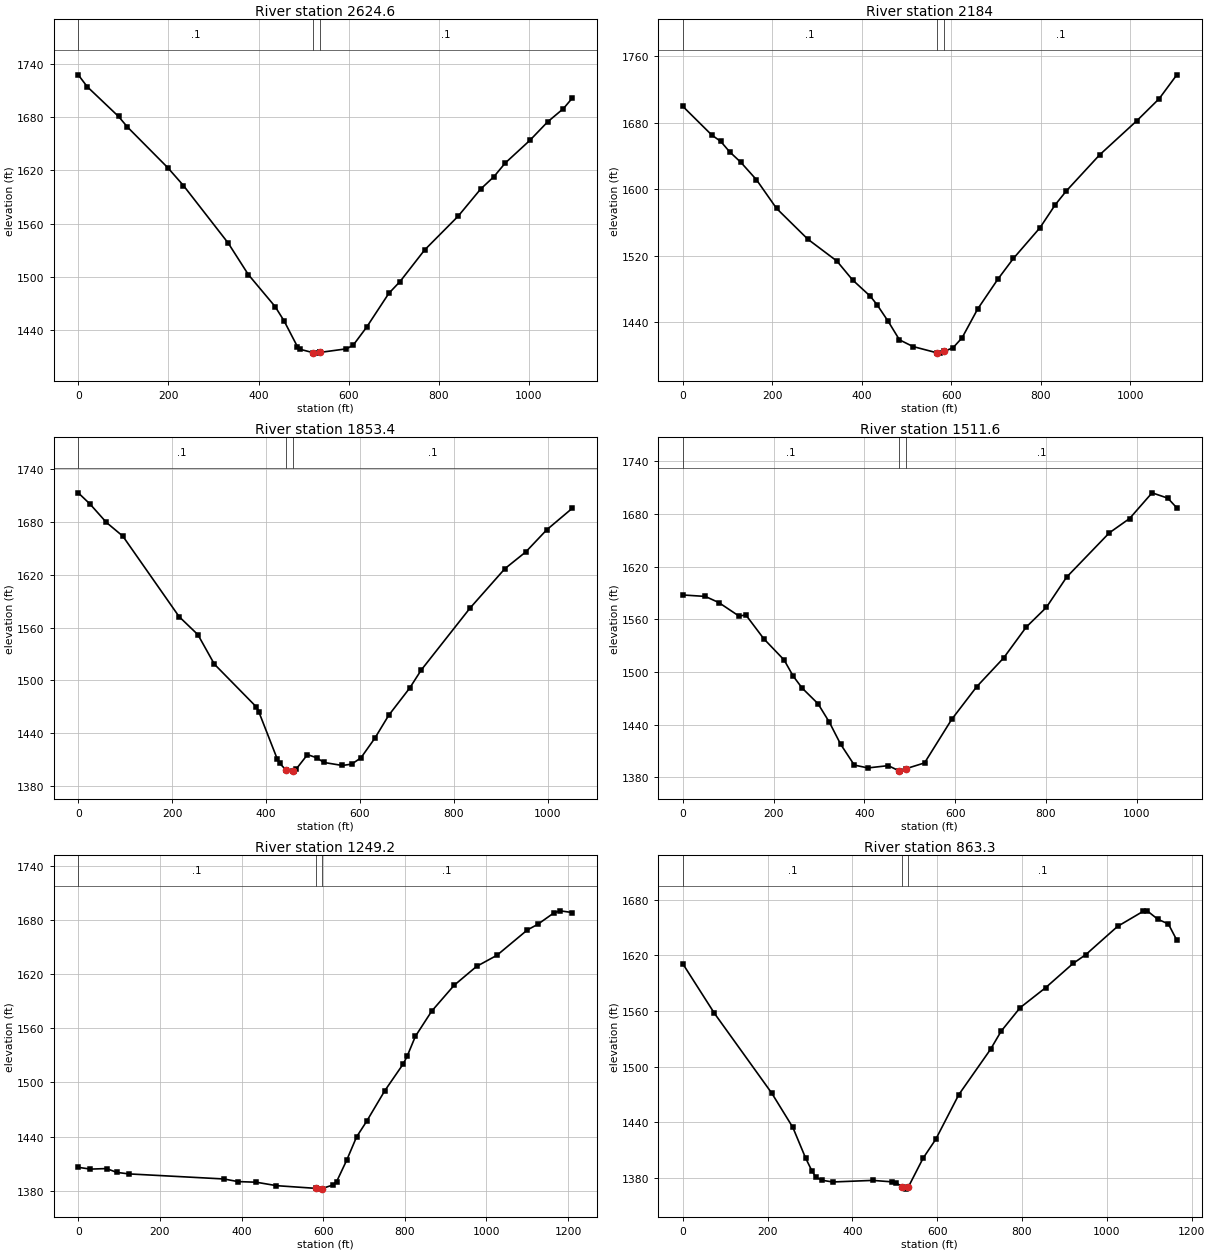
Type RM Length L Ch R = 1 ,2624.6  ,435.6,440.7,445.7
XS GIS Cut Line= 4
     1785715.022       273343.56     1785522.126      273626.748
     1785353.854      273918.145     1785069.143      274222.719
#Sta/Elev= 30
       0  1727.9    19.9 1714.52    89.4 1680.94   109.2 1668.99   198.6 1623.17
   233.4 1603.03   332.7 1538.13   377.3 1502.63   436.7 1466.58   456.5 1450.53
   486.2 1421.39   491.1 1418.48   520.6 1414.57   530.7 1414.01   535.6 1414.75
   535.6 1414.76     595 1418.86   609.9 1422.89   639.6 1443.15   689.1 1481.47
   713.9 1494.74   768.5 1530.39   842.9 1568.49   892.6 1598.98   922.3 1613.08
   947.2 1628.36  1001.8 1653.91  1041.5 1674.91  1076.2 1689.71  1096.1 1701.65
#Mann= 3 , 0 , 0
       0      .1       0   520.6    .045       0   535.6      .1       0
Bank Sta=520.6,535.6
XS Rating Curve= 0 ,0
Exp/Cntr=0.3,0.1

Type RM Length L Ch R = 1 ,2184    ,329.8,330.5,331.3
XS GIS Cut Line= 4
     1785542.647      273220.434     1785222.521      273372.289
     1784968.061      273647.269     1784820.311       273992.02
#Sta/Elev= 30
       0 1699.63    64.9 1665.06    84.8 1657.46   104.8 1644.88   129.8  1632.3
   164.7 1611.33   209.6 1576.87   279.5 1539.88   344.3 1513.67   379.3    1491
   419.3  1471.2   434.2  1461.1   459.2    1441   484.2 1418.96   514.2 1410.91
   569.2 1403.13   574.1 1402.95   584.2 1405.02   604.1  1409.5   624.1 1421.34
     659 1456.02     704 1491.76   738.8 1516.74   798.1 1553.58   832.6 1581.51
   857.3 1598.02   931.3 1641.16  1015.2 1682.54  1064.6 1708.79    1104 1737.46
#Mann= 3 , 0 , 0
       0      .1       0   569.2    .045       0   584.2      .1       0
Bank Sta=569.2,584.2
XS Rating Curve= 0 ,0
Exp/Cntr=0.3,0.1

Type RM Length L Ch R = 1 ,1853.4  ,345.3,341.8,338.4
XS GIS Cut Line= 4
     1785210.208      272953.663     1784980.374      273204.017
     1784738.227      273458.477     1784606.894       273795.02
#Sta/Elev= 30
       0 1713.05      25 1700.35      60 1679.42      95 1663.83   214.9 1572.44
   254.9 1551.98   289.9 1518.55   379.4 1469.95   384.4 1464.74     424 1410.72
   428.9 1406.05   442.4 1398.42   457.4 1397.07   458.6 1397.06   463.5 1398.91
   488.3  1415.8   508.1 1412.22   522.9 1406.94   562.5 1403.47   582.3 1404.98
   602.1  1412.1   631.8 1434.45   661.4  1460.5     706 1491.36   730.7 1511.94
   834.6 1582.21   908.9 1626.97   953.4 1645.99   997.9 1671.04  1052.4 1695.54
#Mann= 3 , 0 , 0
       0      .1       0   442.4    .045       0   457.4      .1       0
Bank Sta=442.4,457.4
XS Rating Curve= 0 ,0
Exp/Cntr=0.3,0.1

Type RM Length L Ch R = 1 ,1511.6  ,269.4,262.4,255.5
XS GIS Cut Line= 4
     1784963.957      272797.704     1784752.302      272926.964
     1784516.602      273261.476     1784423.375       273682.19
#Sta/Elev= 30
       0 1587.77    49.6 1586.11    79.4  1579.1     124 1563.66   138.9 1565.03
   178.6 1537.75   223.2 1513.67     243  1495.4     263 1481.57   297.9 1463.76
   322.9 1442.64   347.8 1417.49   377.8 1393.83   407.7 1390.58   452.6 1393.18
     477 1387.07   477.6 1386.93     492 1389.77   532.5  1396.3   592.3 1445.94
   647.2 1483.09   706.8 1516.04   756.3 1551.09   800.8 1573.63   845.4  1608.1
   939.5 1658.63   984.1 1674.94  1033.6 1704.22  1068.3 1698.14  1088.1 1687.03
#Mann= 3 , 0 , 0
       0      .1       0     477    .045       0     492      .1       0
Bank Sta=477,492
XS Rating Curve= 0 ,0
Exp/Cntr=0.3,0.1

Type RM Length L Ch R = 1 ,1249.2  ,414.4,385.9,357.5
XS GIS Cut Line= 4
     1784783.373       272539.14     1784442.726        272892.1
     1784352.434      273109.621     1784356.538      273593.915
#Sta/Elev= 30
       0 1405.97    29.7 1403.99    69.4 1404.58    94.1 1400.37   123.9 1398.68
   356.8 1393.06   391.4 1390.15     436 1389.48   485.6 1385.65   582.1 1382.67
   588.7 1381.81   597.1 1382.45     623 1386.25   632.8 1389.94   657.4 1413.56
   681.9 1439.66   706.4 1456.84     751 1490.79     796 1520.36   805.9 1529.12
   825.9 1550.97   865.8 1578.87   920.8 1607.54   975.7 1628.44  1025.6 1640.76
  1100.5 1668.95  1125.5 1675.02  1165.4 1687.79  1180.4 1690.06  1210.4 1688.18
#Mann= 3 , 0 , 0
       0      .1       0   582.1    .045       0   597.1      .1       0
Bank Sta=582.1,597.1
XS Rating Curve= 0 ,0
Exp/Cntr=0.3,0.1

Type RM Length L Ch R = 1 ,863.3   ,398.2,405.9,414.1
XS GIS Cut Line= 4
     1783753.616      272703.717     1783941.745      272942.999
     1784220.562      273172.836     1784306.789      273664.501
#Sta/Elev= 30
       0  1610.9    74.8 1557.34   209.6  1471.6   259.5 1434.58   289.4 1401.81
   304.4 1387.75   314.3 1380.69   329.1 1377.54   353.9 1375.75   447.9 1377.47
   492.5 1375.91   502.4  1374.9   516.7 1370.79   527.1 1368.05   531.7 1370.21
   566.7 1401.42   596.4 1421.65   650.9 1469.89   725.6 1518.62   750.6 1538.15
   795.5 1563.54   855.4 1585.02   920.3 1611.18   950.2 1620.65  1025.1 1651.08
    1085 1667.21    1095 1667.88    1120 1658.82  1144.9 1653.77  1164.9 1636.25
#Mann= 3 , 0 , 0
       0      .1       0   516.7    .045       0   531.7      .1       0
Bank Sta=516.7,531.7
XS Rating Curve= 0 ,0
Exp/Cntr=0.3,0.1

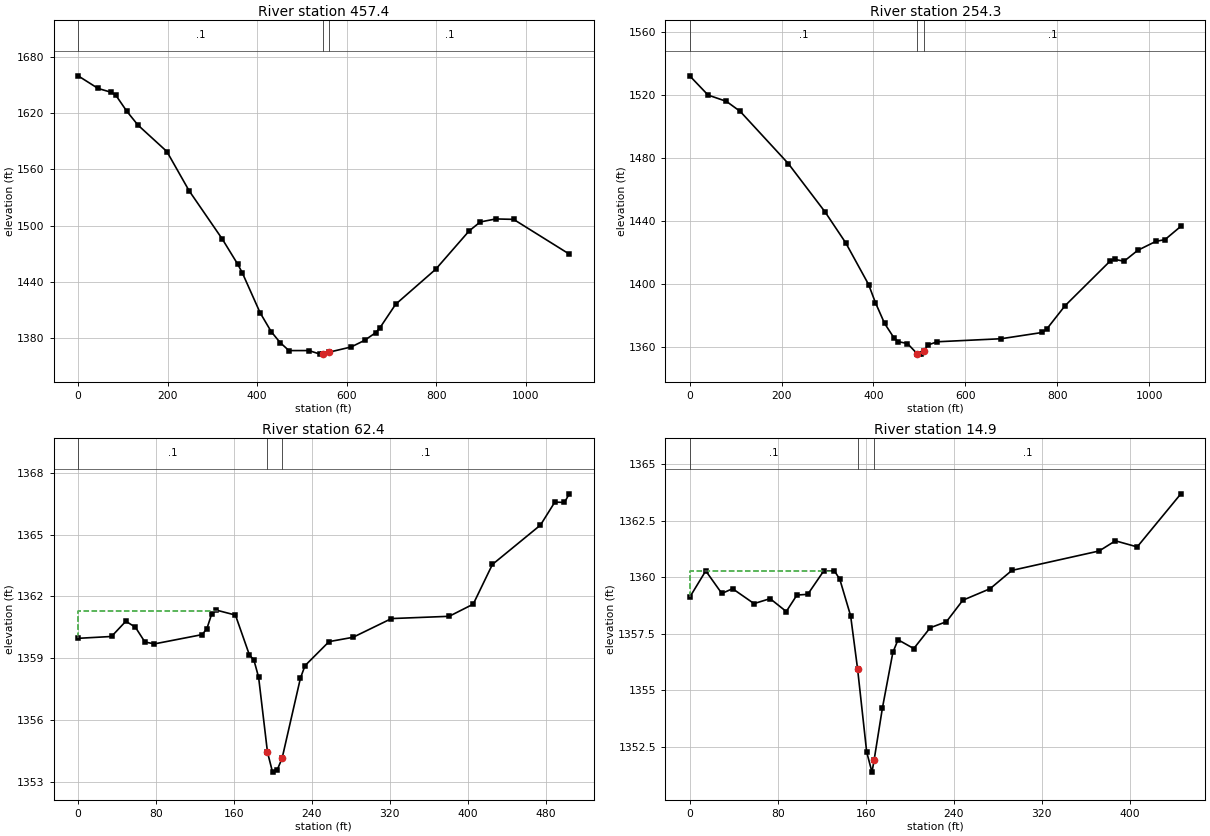
Type RM Length L Ch R = 1 ,457.4   ,204.5,203.2,200.8
XS GIS Cut Line= 3
     1783490.068      272856.611     1783802.507      273303.343
     1784080.921      273779.519
#Sta/Elev= 30
       0  1659.8    44.6 1646.34    74.3 1642.18    84.2 1639.13     109 1621.84
   133.8 1607.18   198.2 1579.05   247.8 1537.24   322.1 1485.56   356.8 1458.51
   366.7 1449.61   406.4 1407.05   431.2 1386.86     451 1375.25   470.8 1366.63
   515.4 1366.65   540.2 1362.85   546.1  1363.2   561.1 1365.01   609.8  1370.5
   639.6 1377.52   664.4 1385.68   674.4 1391.23   709.1 1416.04   798.6 1453.43
   873.1 1494.26     898 1503.87   932.8 1507.09   972.5 1506.64  1096.8  1469.6
#Mann= 3 , 0 , 0
       0      .1       0   546.1    .045       0   561.1      .1       0
Bank Sta=546.1,561.1
XS Rating Curve= 0 ,0
Exp/Cntr=0.3,0.1

Type RM Length L Ch R = 1 ,254.3   ,208.7,191.8,191.9
XS GIS Cut Line= 4
     1783366.137      272996.164      1783535.81      273284.608
     1783766.566      273596.807     1784041.437      273807.202
#Sta/Elev= 30
       0 1532.02      40 1519.83    79.9 1515.84   109.9 1509.49   214.8 1476.35
   294.7 1445.75   339.6 1426.19   389.4 1399.77   404.3 1388.25   424.2 1375.12
   444.2 1366.15   454.1 1363.58     474 1362.37   494.7 1356.03   498.9 1355.67
   503.9 1355.72   509.7 1357.84   518.8 1361.48   538.7  1363.5   678.1 1365.43
   767.4  1369.4   777.3 1371.64   816.8 1386.29   915.7 1414.83   925.6 1415.68
   945.4 1414.53   975.1 1421.43  1014.6 1427.12  1034.4 1428.22    1069 1436.66
#Mann= 3 , 0 , 0
       0      .1       0   494.7    .045       0   509.7      .1       0
Bank Sta=494.7,509.7
XS Rating Curve= 0 ,0
Exp/Cntr=0.3,0.1

Type RM Length L Ch R = 1 ,62.4    ,32.6,47.5,43.1
XS GIS Cut Line= 4
     1783395.738      273375.012     1783454.101      273520.457
     1783518.486      273561.219     1783775.098      273649.226
#Sta/Elev= 30
       0 1359.96    34.3 1360.05      49 1360.79    58.8  1360.5    68.6 1359.78
    78.4 1359.69   127.3 1360.14   132.2 1360.43   137.1 1361.14     142 1361.33
   161.5 1361.09   175.8 1359.16   180.5  1358.9   185.3 1358.07   194.4 1354.43
   199.6 1353.46   204.3 1353.56   209.4 1354.13   228.2 1358.02   232.9 1358.63
   257.6  1359.8   282.2 1360.01   321.7 1360.92   380.9 1361.03   405.6 1361.62
   425.3 1363.55   474.6 1365.46   489.4 1366.58   499.3 1366.56   504.2 1366.98
#Mann= 3 , 0 , 0
       0      .1       0   194.4    .045       0   209.4      .1       0
#XS Ineff= 2 , 0
          143.49 1361.27
Permanent Ineff=
       F       F
Bank Sta=194.4,209.4
XS Rating Curve= 0 ,0
Exp/Cntr=0.3,0.1

Type RM Length L Ch R = 1 ,14.9    ,11.1,14.9,33.8
XS GIS Cut Line= 4
     1783361.461      273419.943     1783447.153      273556.123
     1783483.746      273578.357     1783715.346      273651.079
#Sta/Elev= 30
       0 1359.11    14.6 1360.28    29.2 1359.28      39 1359.49    58.5 1358.83
    73.1 1359.05    87.8 1358.48    97.5 1359.21   107.3 1359.24   121.9 1360.28
   131.6 1360.28   136.5  1359.9   146.3 1358.29   152.6 1355.95   160.9 1352.26
   165.7 1351.37   167.6 1351.89   175.2 1354.21   184.7 1356.67   189.4 1357.23
   203.7 1356.84   218.6 1357.76   233.4 1358.03   248.3 1358.98   273.1 1359.49
   292.9  1360.3   372.2 1361.16     387 1361.61   406.8 1361.34   446.5 1363.69
#Mann= 3 , 0 , 0
       0      .1       0   152.6    .045       0   167.6      .1       0
#XS Ineff= 2 , 0
          128.19 1360.26
Permanent Ineff=
       F       F
Bank Sta=152.6,167.6
XS Rating Curve= 0 ,0
Exp/Cntr=0.3,0.1

Chan Stop Cuts=-1
Use User Specified Reach Order=0